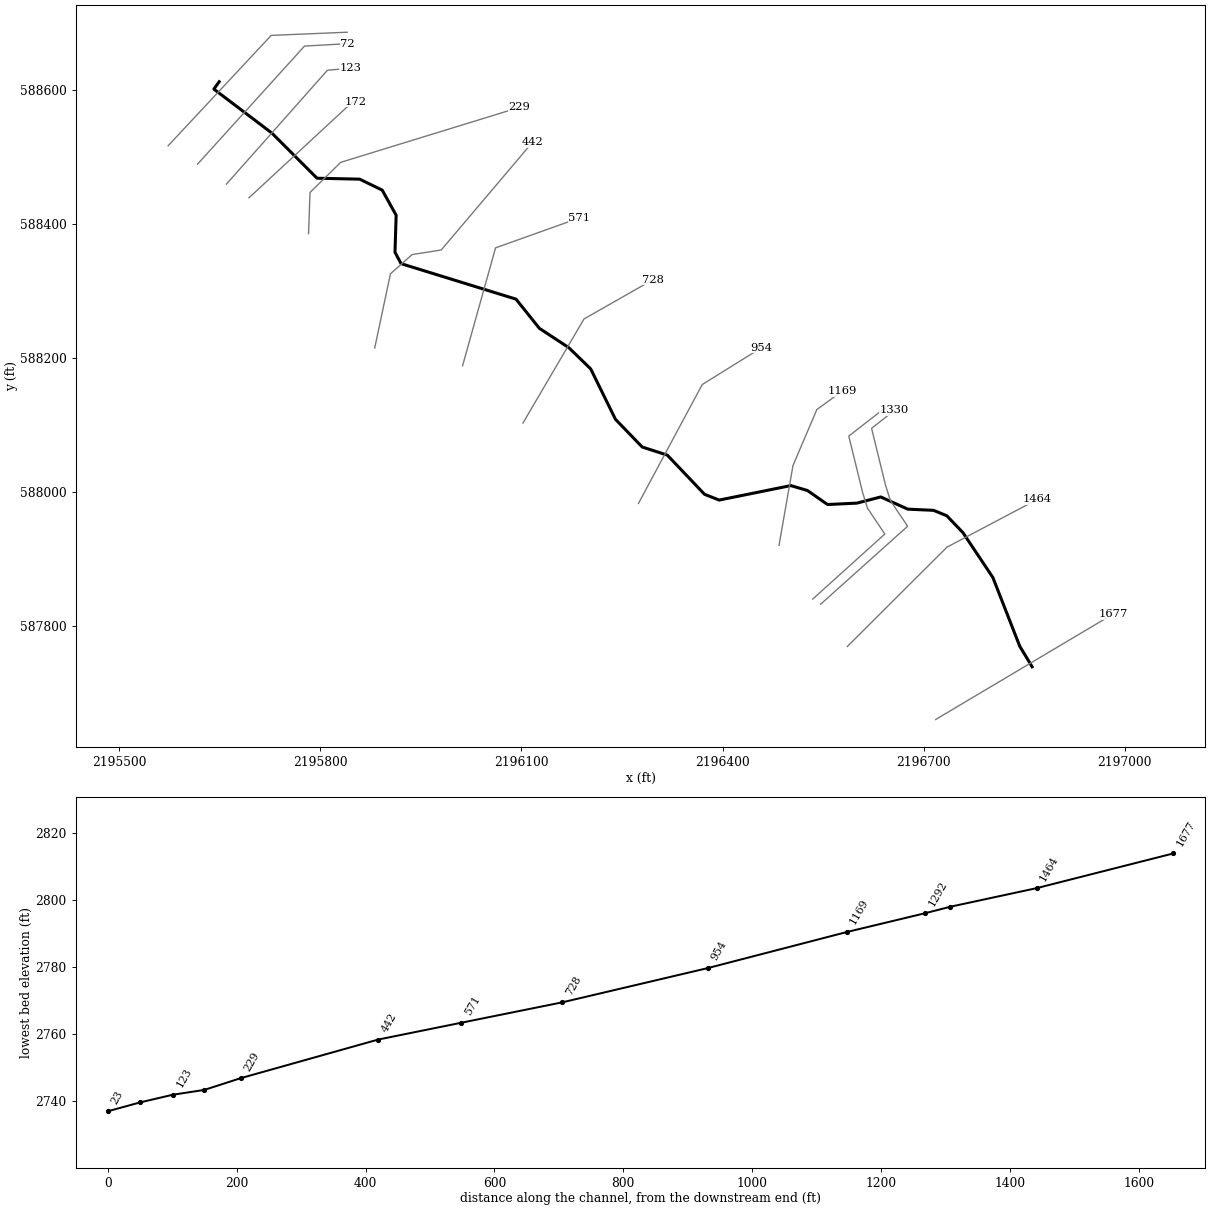
--- ROUGHRN.prj (project) ---

Proj Title=ROUGHRN
Current Plan=p01
Default Exp/Contr=0,0
English Units
Geom File=g01
Flow File=f01
Plan File=p01
BEGIN DESCRIPTION:
----------MODEL BY WOOD PLC 2022----------
AFH study
Randolph County, WV
HEC-RAS Version: RAS 6.2
Vertical Datum: NAVD88
Projection: NAD 1983 StatePlane West Virginia S FIPS 4702 (US Feet)
Terrain: 1-meter LIDAR (FEMA Region III 3DEP collected 2016-2018)
Land Use: 2019 NLCD
Hydrologic Method:
WV SIR2010-5033 regression equations
Additional Model Notes:
None
END DESCRIPTION:
DSS Export Rating Curves= 0
DSS Export Rating Curve Sorted= 0
DSS Export Volume Flow Curves= 0
DXF OffsetX= 0
DXF OffsetY= 0
DXF ScaleX= 0
DXF ScaleY= 0

--- ROUGHRN.p01 (plan) ---

Plan Title=Floodplain
Program Version=6.20
Short Identifier=Floodplain
Geom File=g01
Flow File=f01
Subcritical Flow
K Sum by GR= 0
Std Step Tol= 0.01
Critical Tol= 0.01
Num of Std Step Trials= 20
Max Error Tol= 0.3
Flow Tol Ratio= 0.001
Split Flow NTrial= 30
Split Flow Tol= 0.02
Split Flow Ratio= 0.02
Log Output Level= 0
Friction Slope Method= 1
Unsteady Friction Slope Method= 2
Unsteady Bridges Friction Slope Method= 1
Parabolic Critical Depth
Global Vel Dist= 0 , 0 , 0
Global Log Level= 0
CheckData=True
Encroach Param=-1 ,0,0, 0
Mapping Interval=1HOUR
Computation Time Step Use Courant=        0
Computation Time Step Use Time Series=    0
Computation Time Step Count To Double=0
Computation Time Step Max Doubling=0
Computation Time Step Max Halving=0
Computation Time Step Residence Courant=0
Run HTab= 0
Run UNet= 0
Run Sediment= 0
Run PostProcess= 0
Run WQNet= 0
Run RASMapper=-1
UNET Theta= 0
UNET Theta Warmup= 0
UNET ZTol= 0
UNET ZSATol= 0
UNET MxIter= 0
UNET Max Iter WO Improvement= 0
UNET MaxInSteps= 0
UNET DtIC= 0
UNET DtMin= 0
UNET MaxCRTS= 0
UNET WFStab= 0
UNET SFStab= 0
UNET WFX= 1
UNET SFX= 1
UNET Gravity=32.174
UNET 1D Methodology=Finite Difference
UNET DSS MLevel= 1
UNET Pardiso=0
UNET DZMax Abort= 0
UNET Use Existing IB Tables= 0
UNET Froude Reduction=False
UNET Froude Limit= 0
UNET Froude Power= 0
UNET D1 Cores= 0
UNET WindReference=Eulerian
UNET WindDragFormulation=Hsu (1988)
UNET D2 Coriolis=0
UNET D2 Cores= 0
UNET D2 Theta= 1
UNET D2 Theta Warmup= 1
UNET D2 Z Tol= 0.01
UNET D2 Volume Tol= 0.01
UNET D2 Max Iterations= 20
UNET D2 Equation= 0
UNET D2 RampUpFraction=0.1
UNET D2 TimeSlices= 1
UNET D2 Turbulence Formulation=Non-Conservative (original)
UNET D2 Eddy Viscosity=0.3
UNET D2 Transverse Eddy Viscosity=0.1
UNET D2 Smagorinsky Mixing=0
UNET D2 BCVolumeCheck=0
UNET D2 Cores=0
UNET D2 SolverType=PARDISO (Direct)
UNET D2 Minimum Iterations= 2147483647
UNET D2 Maximum Iterations= 2147483647
UNET D2 Restart Number= 10
UNET D2 Relaxation Coeff=1.3
UNET D2 SOR Precondition Iterations= 10
UNET D2 ILUT Maximum Fill= 8
UNET D2 ILUT Tolerance=1E-08
UNET D1D2 MaxIter= 0
UNET D1D2 ZTol=0.01
UNET D1D2 QTol=0.1
UNET D1D2 MinQTol=1
Write IC File= 0
Write IC File at Fixed DateTime=0
Write IC File at Sim End=0
Echo Input=False
Echo Parameters=False
Echo Output=False
Write Detailed= 0
HDF Write Warmup=0
HDF Write Time Slices=0
HDF Flush=0
HDF Compression= 1
HDF Chunk Size= 1
HDF Spatial Parts= 1
HDF Use Max Rows=0
HDF Fixed Rows= 1
Calibration Method= 0
Calibration Iterations= 20
Calibration Max Change=0.05
Calibration Tolerance=0.2
Calibration Maximum=1.5
Calibration Minimum=0.5
Calibration Optimization Method= 1
WQ AD Non Conservative
WQ ULTIMATE=-1
WQ Max Comp Step=1HOUR
WQ Output Interval=15MIN
WQ Output Selected Increments= 0
WQ Output face flow=0
WQ Output face velocity=0
WQ Output face area=0
WQ Output face dispersion=0
WQ Output cell volume=0
WQ Output cell surface area=0
WQ Output cell continuity=0
WQ Output cumulative cell continuity=0
WQ Output face conc=0
WQ Output face dconc_dx=0
WQ Output face courant=0
WQ Output face peclet=0
WQ Output face adv mass=0
WQ Output face disp mass=0
WQ Output cell mass=0
WQ Output cell source sink temp=0
WQ Output nsm pathways=0
WQ Output nsm derived pathways=0
WQ Create Restart=0
WQ Fixed Restart=0
WQ System Summary=0
WQ Write To DSS=0
Sorting and Armoring Iterations= 10
XS Update Threshold= 0.02
Bed Roughness Predictor= 0
Hydraulics Update Threshold= 0.02
Energy Slope Method= 1
Volume Change Method= 1
Sediment Retention Method= 0
Sediment TS Multiplier= 1
Warm Up Method= 0
XS Weighting Method= 0
Number of US Weighted Cross Sections= 1
Number of DS Weighted Cross Sections= 1
Upstream XS Weight=0
Main XS Weight=1
Downstream XS Weight=0
Number of DS XS's Weighted with US Boundary= 1
Upstream Boundary Weight= 1
Weight of XSs Associated with US Boundary= 0
Number of US XS's Weighted with DS Boundary= 1
Downstream Boundary Weight= 0.5
Weight of XSs Associated with DS Boundary= 0.5
Percentile Method= 0
Sediment Output Level= 3
Mass or Volume Output= 0
Output Increment Type= 1
Profile and TS Output Increment= 1
Transport Output Increment 1
XS Output Flag= 0
XS Output Increment= 10
Read HDF5 Sediment Hotstart= 0
Sediment Hotstart Type= 0
Write Gradation File= 0
Read Gradation Hotstart= 0
Write HDF5 File= 1
Write Binary Output= 1
Write DSS Sediment File= 0
DSS Sediment Output Type= 1
SV Curve= 0
Specific Gage Flag= 0
Subcell Erosion Methods= 0
Subcell Deposition Methods= 0
Advection Scheme= 1
Matrix Solver= 0
Implicit Weighting Factor= 1
Maximum Outer Loop Convergence Iterations= 5
Convergence Maximum Absolute= 0.001
Convergence RMSE= 0.0001
Grain Fractions Max Abs Error= 0.001
Max Subgrid Regions= 1
Max Subgrid Length Scale= 3.402823E+38
Initial Layer Thickness= 3.402823E+38
Min Layer Thickness= 3.402823E+38
Max Layer Thickness= 3.402823E+38
Number of Layers= 5

--- ROUGHRN.f01 (steady flow) ---

Flow Title=Flow
Program Version=6.20
Number of Profiles= 1
Profile Names=P100yr
River Rch & RM=ROUGHRN,Main,1677
     322
Boundary for River Rch & Prof#=ROUGHRN,Main            , 1
Up Type= 0
Dn Type= 3
Dn Slope=0.05225
DSS Import GetInterval= 0
DSS Import GetPeak= 0
DSS Import FillOption= 0

--- ROUGHRN.g01 (geometry) ---

Geom Title=Geometry
Program Version=6.20

River Reach=ROUGHRN         ,Main
Reach XY= 30
2196861.89149445587739.9167810232196843.46972381 587770.46052666
2196803.27130087587873.1971327812196758.64330088587940.026132792
2196734.51530087587965.2591327882196714.72630088587973.280132771
2196676.33330089587975.0411328082196636.08085783587993.248962705
2196600.39719633  587984.02742642196556.59721981587981.948826277
2196526.79433546588002.8247534872196501.84617318588010.203818823
2196395.04821705587988.5961339132196373.13196467 587997.18676794
2196317.62245527588055.6502827622196280.17242275588067.754933201
2196240.25711317588109.0685313522196203.25330091588184.362132788
2196170.59330086588216.009132788 2196126.7063009588244.847132787
2196091.85530087588288.3861327772195920.32630087588341.353132769
2195911.29830088588358.3671327832195913.03430085588413.576132774
 2195892.2013009588451.0751327722195858.52030091588467.395132795
2195794.97930087588468.7841327942195727.61730088 588536.14513278
2195641.04590755588601.757754263     2195648.974      588612.769

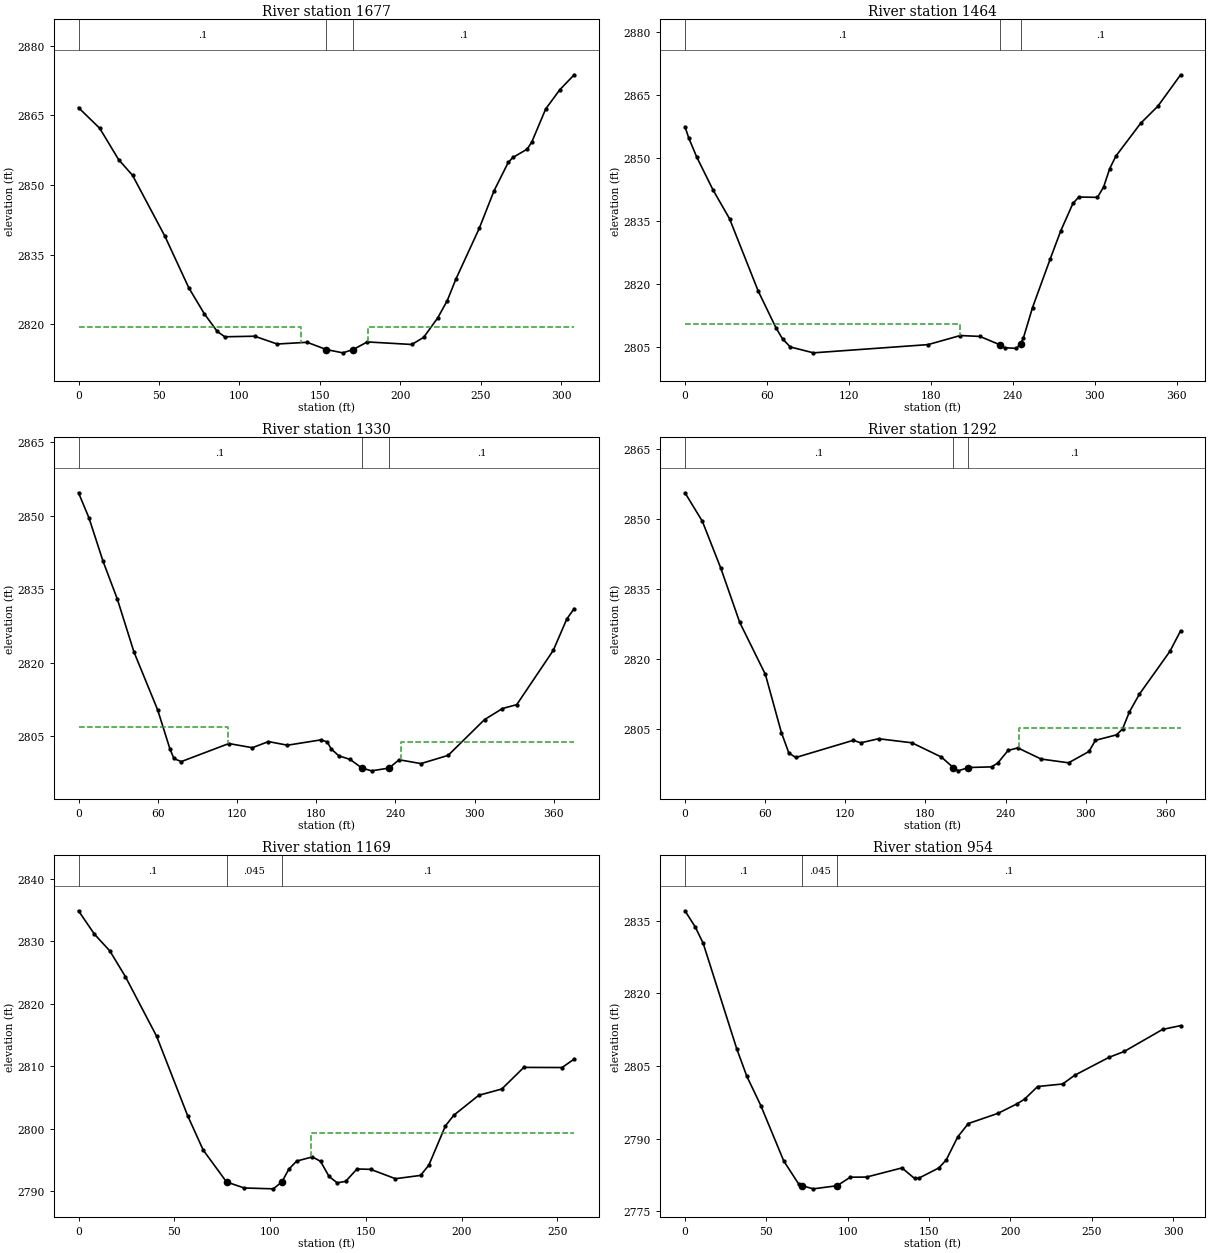
Type RM Length L Ch R = 1 ,1677    ,212.5,212.5,212.5
XS GIS Cut Line= 2
2196718.05493915587661.2251087752196982.85329616587818.641055109
#Sta/Elev= 30
       0 2866.66    13.2 2862.21    24.9 2855.49    33.6 2852.08    53.7 2838.97
    68.6 2827.83    78.2 2822.28    86.2 2818.48    90.9 2817.32   109.5 2817.44
   123.5 2815.76   142.1 2816.13  154.132814.562   164.3 2813.86  170.682814.562
   179.5 2816.21   207.2 2815.66   214.6 2817.21   223.3  2821.4   229.2  2825.1
   234.7 2829.83   249.1 2840.67   258.3 2848.76   267.1 2854.85     270 2855.93
   278.8 2857.71   281.7 2859.21   290.4 2866.38   299.2 2870.53   308.1 2873.74
#Mann= 3 ,-1,0
       0      .1       0  154.13    .045       0  170.68      .1       0
#XS Ineff= 2 , 0
          138.23 2819.53  179.68         2819.42
Permanent Ineff=
       F       F
Bank Sta=154.13,170.68
XS Rating Curve= 0 ,0
Exp/Cntr=0.3,0.1

Type RM Length L Ch R = 1 ,1464    ,134.2,134.2,134.2
XS GIS Cut Line= 3
2196586.17997593587770.1700239962196734.85427651587918.321353748
2196870.07204551587989.787901367
#Sta/Elev= 30
       0 2857.39     2.8 2854.64     8.5 2850.22    20.5 2842.32    32.6 2835.46
    53.6 2818.22    66.6 2809.46    71.4 2806.83    77.1  2804.9      94  2803.5
   177.9 2805.46   201.5 2807.62   215.9 2807.41   230.82805.377     234 2804.71
   242.6 2804.57   245.62805.625   247.6 2806.93   254.4  2814.3   267.4 2825.92
   275.1  2832.6     284 2839.12   288.3 2840.62   301.9 2840.54   306.4 2842.99
   310.9 2847.39   315.4 2850.36   333.5 2858.17   346.2 2862.28   362.8 2869.74
#Mann= 3 ,-1,0
       0      .1       0   230.8    .045       0   245.6      .1       0
#XS Ineff= 2 , 0
          201.59 2810.35
Permanent Ineff=
       F       F
Bank Sta=230.8,245.6
XS Rating Curve= 0 ,0
Exp/Cntr(USF)=0,0
Exp/Cntr=0.3,0.1

Type RM Length L Ch R = 1 ,1330    ,38.4,38.4,38.4
XS GIS Cut Line= 6
2196546.29656303587833.1456165842196676.15799516587949.528650975
2196650.31463254587988.0299871262196642.93081465588011.763687492
2196622.36160767588095.622762122 2196656.5892313588122.530807827
#Sta/Elev= 30
       0  2854.7     7.9 2849.59    18.6 2840.71    29.4 2833.01      42 2822.21
      60 2810.36    69.3 2802.39    72.3 2800.47    77.8 2799.83   113.9 2803.52
   131.7 2802.67   143.9 2803.92   158.3 2803.18   183.6 2804.27   188.4 2803.86
   191.4 2802.43   197.2 2801.02   205.8 2800.27   214.72798.521     222 2797.95
   235.22798.512   242.9 2800.21   259.4 2799.43     280  2801.1   307.6 2808.41
   321.2 2810.67     332 2811.46   359.7 2822.55   369.9 2828.93   375.5 2831.07
#Mann= 3 ,-1,0
       0      .1       0   214.7    .045       0   235.2      .1       0
#XS Ineff= 2 , 0
          112.92 2806.88  244.62         2803.88
Permanent Ineff=
       F       F
Bank Sta=214.7,235.2
XS Rating Curve= 0 ,0
Exp/Cntr(USF)=0,0
Exp/Cntr=0.3,0.1

Type RM Length L Ch R = 1 ,1292    ,122.1,122.1,122.1
XS GIS Cut Line= 6
2196534.54691631587840.8810448522196642.13969131587937.925508574
2196616.29632868587976.4268447242196608.91251079588000.160545091
2196588.34330381 588084.019619722196642.49551541588126.142701723
#Sta/Elev= 30
       0 2855.63      13 2849.53    26.9 2839.41      41 2827.85    60.2 2816.71
    72.2 2804.24    77.8 2799.85      83 2798.91     126 2802.59   131.6 2802.05
   144.9 2802.93   169.9 2802.06     192    2799   200.9 2796.74   204.6 2796.05
  212.16 2796.76   229.5  2796.9   234.1  2797.7   241.9 2800.41   249.2 2800.97
   266.6 2798.58   287.2 2797.77   302.5  2800.2   307.3 2802.59   323.1 2803.76
   327.6 2805.02   332.7 2808.65   340.2 2812.47   363.1 2821.67   371.1 2826.07
#Mann= 3 ,0,0
       0      .1       0   200.9    .045       0  212.16      .1       0
#XS Ineff= 2 , 0
                          250.11         2805.33
Permanent Ineff=
       F       F
Bank Sta=200.9,212.16
XS Rating Curve= 0 ,0
Exp/Cntr(USF)=0,0
Exp/Cntr=0.3,0.1

Type RM Length L Ch R = 1 ,1169    ,215.8,215.8,215.8
XS GIS Cut Line= 4
2196484.25525046587921.0244979922196505.07874596588039.997941516
2196540.70246858588123.6746352682196578.79911187588151.323090134
#Sta/Elev= 30
       0 2834.91     8.3 2831.17    16.4 2828.47    24.5 2824.36    40.8 2814.82
      57 2802.11    65.1 2796.63    77.3 2791.52    86.5 2790.56   101.7 2790.42
  106.21 2791.53   109.8 2793.56   113.9 2794.86   122.1 2795.53   126.4 2794.82
   130.8  2792.4   135.1 2791.38   139.5 2791.62   145.4  2793.6   152.5 2793.54
   165.5 2792.04   178.6 2792.57   182.9  2794.2   191.6 2800.51     196 2802.21
     209 2805.39     221 2806.39   232.5 2809.85   252.5 2809.83   258.8 2811.18
#Mann= 3 ,0,0
       0      .1       0    77.3    .045       0  106.21      .1       0
#XS Ineff= 2 , 0
                          121.52         2799.32
Permanent Ineff=
       F       F
Bank Sta=77.3,106.21
XS Rating Curve= 0 ,0
Exp/Cntr(USF)=0,0
Exp/Cntr=0.3,0.1

Type RM Length L Ch R = 1 ,954     ,225.5,225.5,225.5
XS GIS Cut Line= 3
2196274.60467101587983.6491613352196369.68249222588160.936728576
2196457.59063401588215.592551262
#Sta/Elev= 30
       0 2837.06     6.3 2833.73    11.2 2830.34    31.8  2808.6      38 2802.92
    46.6 2796.87    60.7 2785.44    69.8 2780.71   71.95 2780.31    78.9 2779.67
   93.53 2780.31   101.6 2782.07   111.6  2782.1   133.4 2783.99   141.1 2781.82
   144.1 2781.93   156.1 2783.99   160.6 2785.64   167.7  2790.4   174.2 2793.15
   192.4 2795.25   204.1 2797.21   208.8 2798.19   216.8 2800.79   232.2 2801.31
   239.5  2803.1   260.6  2806.8     270 2808.02   293.6 2812.57   304.7 2813.36
#Mann= 3 ,0,0
       0      .1       0   71.95    .045       0   93.53      .1       0
Bank Sta=71.95,93.53
XS Rating Curve= 0 ,0
Exp/Cntr(USF)=0,0
Exp/Cntr=0.3,0.1

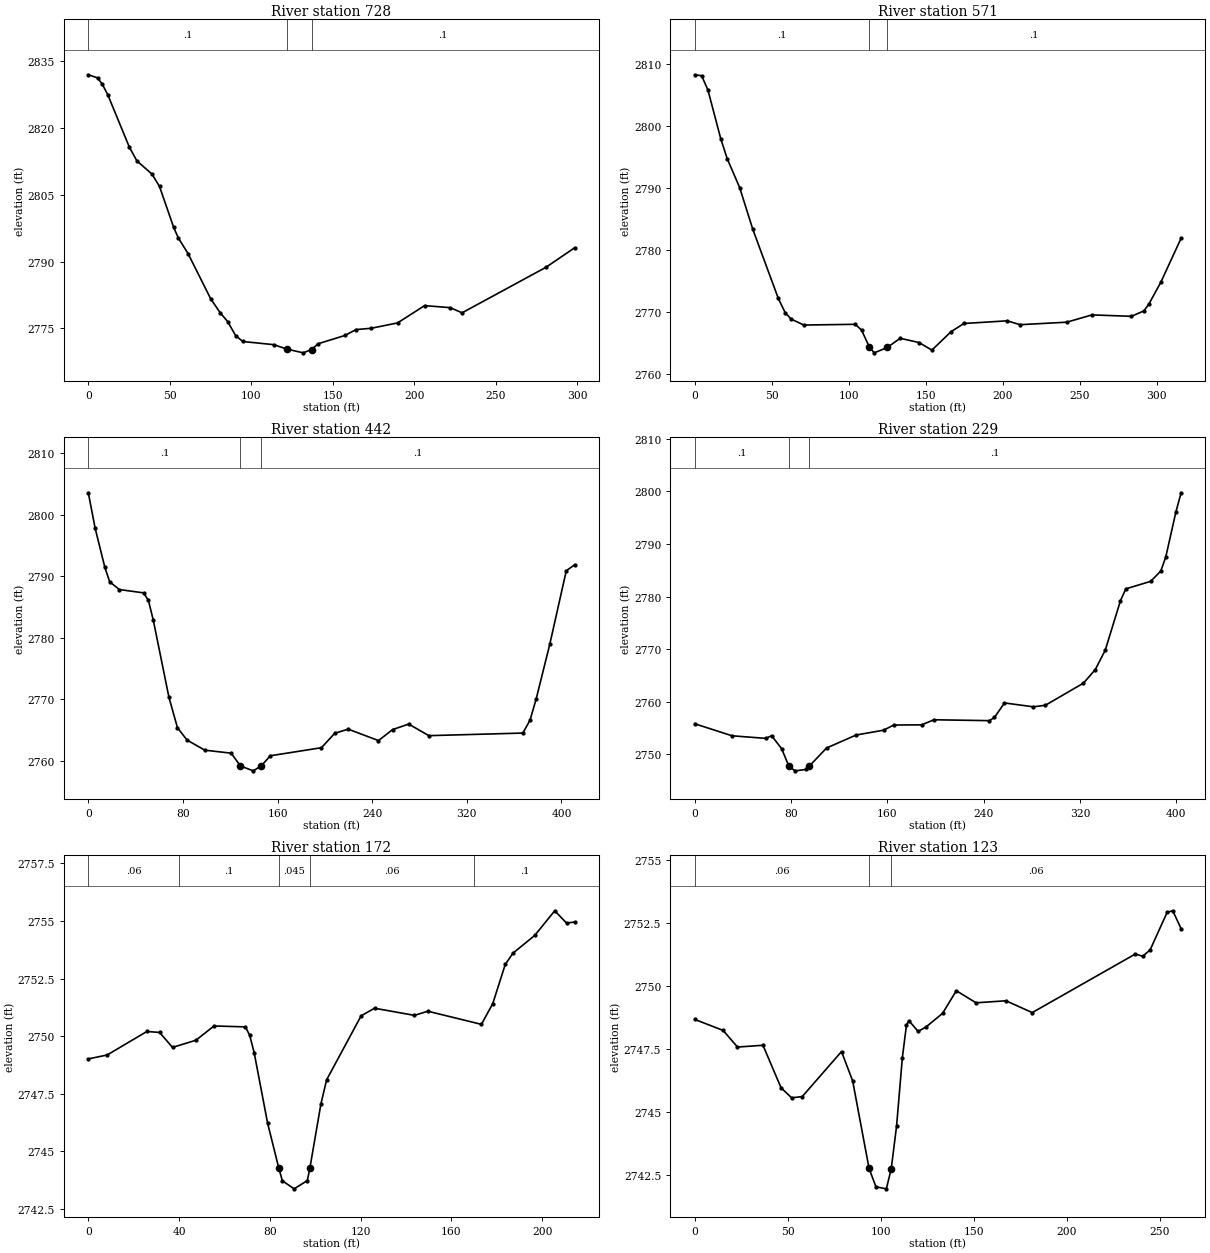
Type RM Length L Ch R = 1 ,728     ,157,157,157
XS GIS Cut Line= 3
2196102.16957802 588103.437756522196193.31512838588258.806912651
2196296.22610785588317.390498471
#Sta/Elev= 30
       0    2832     5.7 2831.31     8.6 2829.86    11.9 2827.56    25.2 2815.72
    29.8 2812.65    39.1 2809.66    43.7 2806.89    52.4 2797.68    55.3 2795.27
    61.2 2791.81    75.1 2781.64    80.9 2778.51    85.5 2776.52    90.4 2773.37
    94.8 2772.03   113.8 2771.32   121.72770.339   131.9 2769.48     1372770.229
   141.1 2771.53   157.6  2773.4   164.3 2774.71   173.6    2775   189.8 2776.21
   206.4  2780.1   222.1 2779.64   229.4 2778.48   280.8  2788.7   298.5 2793.11
#Mann= 3 ,-1,0
       0      .1       0   121.7    .045       0     137      .1       0
Bank Sta=121.7,137
XS Rating Curve= 0 ,0
Exp/Cntr(USF)=0,0
Exp/Cntr=0.3,0.1

Type RM Length L Ch R = 1 ,571     ,128.7,128.7,128.7
XS GIS Cut Line= 3
2196012.09654965588188.8805247962196061.36820565588364.919101837
2196186.60841341588409.622089241
#Sta/Elev= 30
       0 2808.31     4.5 2808.16     8.6 2805.84    16.9 2797.99    21.1 2794.76
    29.2 2790.08    37.7 2783.36    54.3 2772.17    58.7  2769.9    62.6 2768.84
    70.9 2767.88   104.2    2768   108.3 2767.08   113.42764.326   116.6 2763.39
   125.12764.267   133.4 2765.74   145.7 2765.05     154 2763.83   166.5 2766.82
   174.8 2768.13   202.8 2768.56   211.3 2767.94   241.5 2768.34     258 2769.52
   283.5 2769.29   291.6 2770.16   294.8 2771.23   302.6 2774.78   315.8  2781.9
#Mann= 3 ,-1,0
       0      .1       0   113.4    .045       0   125.1      .1       0
Bank Sta=113.4,125.1
XS Rating Curve= 0 ,0
Exp/Cntr(USF)=0,0
Exp/Cntr=0.3,0.1

Type RM Length L Ch R = 1 ,442     ,213.8,213.8,213.8
XS GIS Cut Line= 5
2195881.02929368588215.4628921152195904.52906385 588326.17292047
2195936.90652497588354.894861789 2195980.2505455588361.683684282
2196116.54921249588522.526555665
#Sta/Elev= 30
       0 2803.59     5.8 2797.82      14 2791.46    18.1 2789.11    26.3 2787.86
    46.7 2787.32    50.8 2786.11    54.9 2782.92    68.2 2770.32    75.4 2765.39
    83.5 2763.39    98.5 2761.75   120.8 2761.26  128.64 2759.18   139.4 2758.39
   146.2 2759.19   153.9 2760.84   197.1 2762.15   208.4 2764.51   219.8 2765.16
   245.3 2763.31   257.3  2765.1   270.9 2765.99   287.9 2764.11   367.4 2764.53
   373.5 2766.65   378.7 2770.13   390.1 2778.93   404.1 2790.92   411.2 2791.89
#Mann= 3 ,-1,0
       0      .1       0  128.64    .045       0   146.2      .1       0
Bank Sta=128.64,146.2
XS Rating Curve= 0 ,0
Exp/Cntr(USF)=0,0
Exp/Cntr=0.3,0.1

Type RM Length L Ch R = 1 ,229     ,56.3,56.3,56.3
XS GIS Cut Line= 4
2195782.33522321588386.0849806492195784.49437818588447.489459324
2195830.37435263588492.5004150932196096.38580412588574.317831054
#Sta/Elev= 30
       0 2755.81    31.1 2753.52    59.1 2753.03    63.9 2753.54    72.2 2751.07
   78.31 2747.71    83.4 2746.86    92.4 2747.12   95.24 2747.77   109.5  2751.2
   134.1 2753.67   156.9 2754.59   165.3 2755.57   188.5  2755.6   198.7 2756.57
   244.8  2756.4     249 2757.02   257.3 2759.77   281.3 2759.03   291.3 2759.33
   322.9 2763.53   332.7  2766.1     341  2769.8   353.6 2779.18   358.1 2781.46
   378.7 2782.88   387.1 2784.83   391.2 2787.44   399.7 2796.09     404 2799.72
#Mann= 3 ,0,0
       0      .1       0   78.31    .045       0   95.24      .1       0
Bank Sta=78.31,95.24
XS Rating Curve= 0 ,0
Exp/Cntr=0.3,0.1

Type RM Length L Ch R = 1 ,172     ,48.8,48.8,48.8
XS GIS Cut Line= 3
2195693.40449337588439.5303657522195847.46166186588582.170903693
2195851.73389008 588582.73408316
#Sta/Elev= 30
       0 2749.01     8.3 2749.18    25.8  2750.2    31.4 2750.16    37.1 2749.51
    47.4 2749.82    55.4 2750.44    69.2  2750.4    71.1 2750.04    73.1 2749.27
      79 2746.22    83.92744.281    85.5 2743.72    90.7 2743.37    96.5 2743.73
    97.62744.256   102.5 2747.06     105  2748.1   120.2 2750.88   126.1 2751.21
   143.7  2750.9   149.6 2751.08   173.2 2750.51   178.2 2751.41   183.7 2753.11
   187.1  2753.6   196.7 2754.37   205.5 2755.44   210.7 2754.91   214.3 2754.95
#Mann= 5 ,-1,0
       0     .06       0      40      .1       0    83.9    .045       0
    97.6     .06       0     170      .1       0
Bank Sta=83.9,97.6
XS Rating Curve= 0 ,0
Exp/Cntr(USF)=0,0
Exp/Cntr=0.3,0.1

Type RM Length L Ch R = 1 ,123     ,51,51,51
XS GIS Cut Line= 3
2195659.82000401588460.0042999792195810.54012905588629.936660739
 2195844.6762965588632.827496253
#Sta/Elev= 30
       0 2748.68    15.3 2748.24      23 2747.58    36.7 2747.65    46.4 2745.96
    52.1 2745.56    57.8 2745.61    78.9  2747.4    84.9 2746.23    93.72742.753
    97.4 2742.02     103 2741.94  105.62 2742.74   108.5 2744.44   111.6 2747.16
   113.8 2748.45   115.1 2748.63   120.1  2748.2   124.5 2748.39   133.2 2748.92
   140.6 2749.82   151.2 2749.34   167.3 2749.42   181.4 2748.95   236.8 2751.28
   240.8 2751.19   244.8 2751.45   253.9 2752.94   256.9    2753   261.4 2752.29
#Mann= 3 ,-1,0
       0     .06       0    93.7    .045       0  105.62     .06       0
Bank Sta=93.7,105.62
XS Rating Curve= 0 ,0
Exp/Cntr(USF)=0,0
Exp/Cntr=0.3,0.1

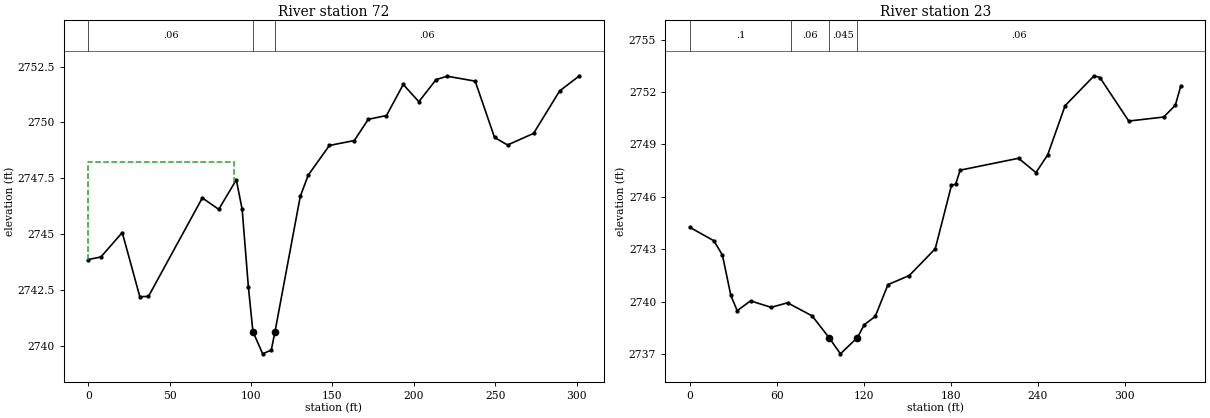
Type RM Length L Ch R = 1 ,72      ,49.8,49.8,49.8
XS GIS Cut Line= 3
 2195616.7240679588489.7963083382195776.28798564588665.919323986
2195840.32868545588669.534791531
#Sta/Elev= 30
       0 2743.86     7.7 2743.98    20.8 2745.07    31.6  2742.2    36.9 2742.21
      70 2746.62    80.1 2746.11    90.9 2747.43    94.5 2746.11    98.3 2742.65
   101.1 2740.64   107.1 2739.64   112.4 2739.81  114.67 2740.63   130.2 2746.69
   135.1 2747.64   148.1 2748.97   163.4 2749.19     172 2750.14   183.2 2750.31
   193.5  2751.7   203.1 2750.93   213.7 2751.92   220.5 2752.07   237.7 2751.85
   249.6 2749.33   257.6 2748.99   273.6 2749.51   289.6 2751.41   301.8 2752.09
#Mann= 3 ,-1,0
       0     .06       0   101.1    .045       0  114.67     .06       0
#XS Ineff= 2 , 0
           89.71 2748.25
Permanent Ineff=
       F       F
Bank Sta=101.1,114.67
XS Rating Curve= 0 ,0
Exp/Cntr(USF)=0,0
Exp/Cntr=0.3,0.1

Type RM Length L Ch R = 1 ,23      ,,,
XS GIS Cut Line= 3
2195572.83797107588517.2537320812195726.63630632588681.884847896
2195839.98689902 588686.61472763
#Sta/Elev= 30
       0 2744.26    16.6 2743.49    22.5 2742.67    28.3 2740.36    32.7 2739.49
    41.9 2740.05    56.1 2739.68    67.4 2739.94    84.4 2739.19    96.2 2737.93
   103.9 2737.02  115.63 2737.95   120.3 2738.68   127.9 2739.16   136.7 2740.98
   151.4  2741.5   169.3 2743.03   180.5 2746.66   183.4 2746.73   186.5 2747.53
   226.8 2748.21   238.8 2747.39   246.9 2748.41   258.9 2751.22   278.9 2752.93
   282.9 2752.83   302.8 2750.34   326.9 2750.57   334.9 2751.24338.7431 2752.36
#Mann= 4 ,-1,0
       0      .1       0      70     .06       0    96.2    .045       0
  115.63     .06       0
Bank Sta=96.2,115.63
XS Rating Curve= 0 ,0
Exp/Cntr(USF)=0,0
Exp/Cntr=0.3,0.1
LCMann Table=0

Chan Stop Cuts=-1
Use User Specified Reach Order=0
Composite Channel Slope=5